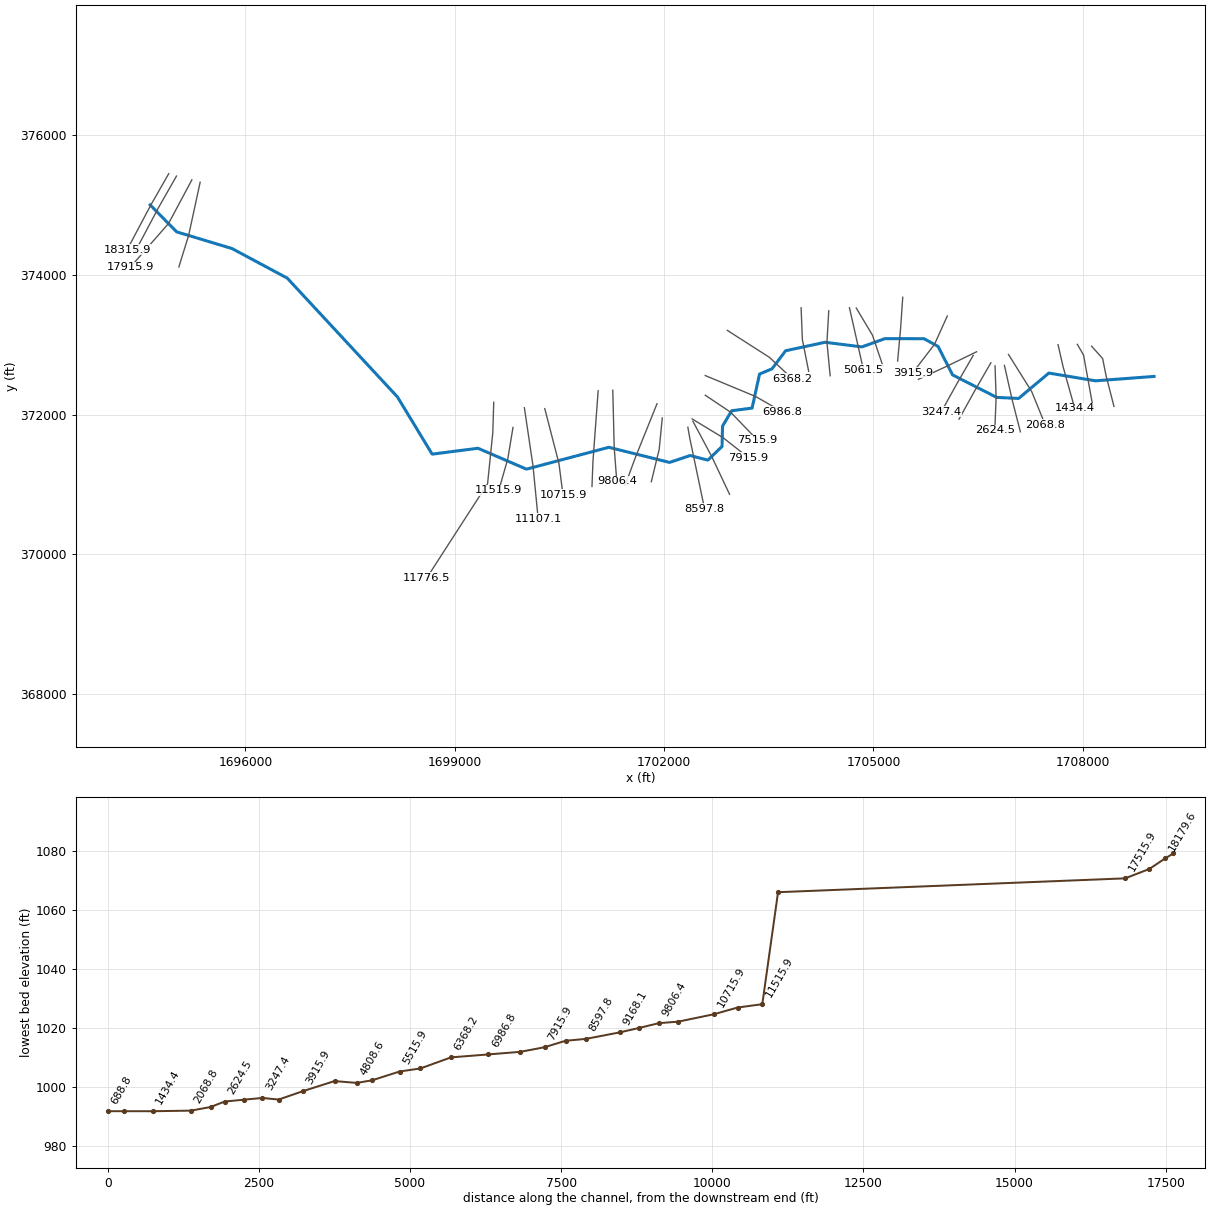
--- OwnDvyFrk.prj (project) ---

Proj Title=OwnDvyFrk
Current Plan=p01
Default Exp/Contr=0,0
English Units
Geom File=g01
Flow File=f01
Plan File=p01
BEGIN DESCRIPTION:
END DESCRIPTION:
DSS Export Rating Curves= 0
DSS Export Rating Curve Sorted= 0
DSS Export Volume Flow Curves= 0
DXF OffsetX= 0
DXF OffsetY= 0
DXF ScaleX= 0
DXF ScaleY= 0

--- OwnDvyFrk.p01 (plan) ---

Plan Title=Floodplain
Program Version=4.00
Geom File=g01
Flow File=f01
K Sum by GR=0
Std Step Tol=0.01
Critical Tol=0.01
Num of Std Step Trials=20
Max Error Tol=0.3
Flow Tol Ratio=0.001
Split Flow NTrial=30
Split Flow Tol=0.02
Split Flow Ratio=0.02
Log Output Level=0
Friction Slope Method=1
Unsteady Friction Slope Method=2
Unsteady Bridges Friction Slope Method=1
Global Log Level=0
CheckData=False
Run HTab=0
Run UNet=0
Run PostProcess=0
UNET Theta=0
UNET Theta Warmup=0
UNET ZTol=0
UNET ZSATol=0
UNET MxIter=0
UNET MaxInSteps=0
UNET DtIC=0
UNET DtMin=0
UNET MaxCRTS=0
UNET WFStab=0
UNET SFStab=0
UNET WFX=0
UNET SFX=0
UNET DSS MLevel=0
UNET DZMax Abort=0
UNET Convert EG Bridges=0
UNET Use Existing IB Tables=0
UNET Froude Limit=0
UNET Froude Power=0
Write IC File=0
Echo Input=False
Echo Output=False
Write Detailed=0

--- OwnDvyFrk.f01 (steady flow) ---

Flow Title=NFF Regression Equation
Program Version=4.00
Number of Profiles=1
Profile Names=P100yr
River Rch & RM=OwnDvyFrk,Main      ,18315.9
500.7017
River Rch & RM=OwnDvyFrk,Main      ,17915.9
     722
River Rch & RM=OwnDvyFrk,Main      ,17515.9
747.4272
River Rch & RM=OwnDvyFrk,Main      ,11776.5
1253.115
River Rch & RM=OwnDvyFrk,Main      ,8261.4
1339.363
River Rch & RM=OwnDvyFrk,Main      ,7915.9
1632.736
River Rch & RM=OwnDvyFrk,Main      ,6368.2
1657.164
River Rch & RM=OwnDvyFrk,Main      ,5862.4
1913.600
River Rch & RM=OwnDvyFrk,Main      ,688.8
2025.910
Boundary for River Rch & Prof#=OwnDvyFrk,Main      ,1
Up Type=0
Dn Type=3
Dn Slope=0.003122

--- OwnDvyFrk.g01 (geometry) ---

Geom Title=USGS 3m DEM
Program Version=4.00

River Reach=OwnDvyFrk       ,Main
Reach XY= 30
     1694634.814       374999.33     1695014.832      374613.642
     1695808.578      374374.574     1696599.237      373952.191
     1698179.284      372252.143     1698675.701      371434.963
     1699332.501      371518.972     1700027.481      371220.376
     1701207.887      371532.815     1702078.265      371316.463
      1702374.14      371414.719     1702626.104      371348.935
     1702829.874      371544.764     1702836.945      371835.778
     1702968.315      372055.449     1703260.237      372093.426
     1703367.113      372580.751     1703546.186      372654.962
     1703740.471      372913.304      1704305.04      373034.301
     1704834.556        372968.7     1705162.857      373086.374
     1705723.031      373085.689     1705925.529      372975.325
     1706132.854      372568.148     1706764.779      372246.467
     1707079.412      372231.251     1707511.964      372594.025
     1708180.742      372483.584     1709020.275       372545.99

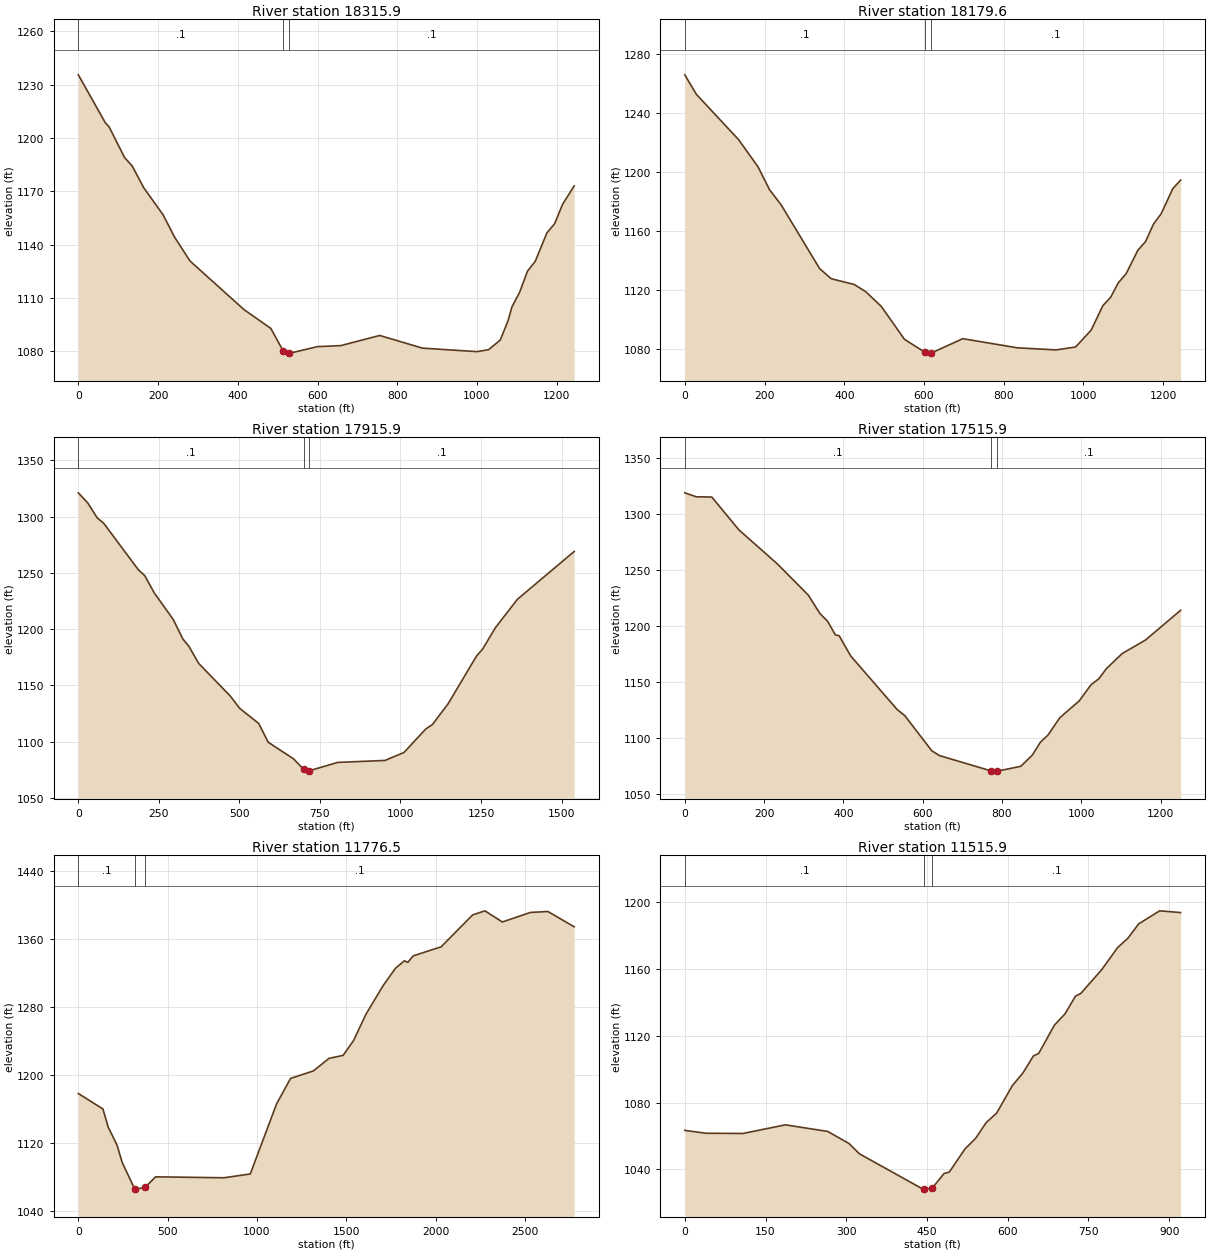
Type RM Length L Ch R = 1 ,18315.9 ,131.742,136.259,140.123
XS GIS Cut Line= 3
     1694901.319      375445.718     1694642.398      374992.812
     1694303.648      374355.229
#Sta/Elev= 30
       0 1235.62    67.6 1208.71    77.3 1206.33   115.9 1189.11   135.3 1184.27
   164.2 1172.06   212.5 1156.93   241.5 1144.31   280.2 1130.88   415.4 1103.58
     483 1092.96   514.2 1080.15   529.2 1079.09   531.4 1079.08   599.7 1082.73
   658.3  1083.3   755.9 1089.02   863.2 1081.89   999.8 1079.92    1029 1081.01
  1058.3 1086.41  1077.8 1097.26  1087.6 1105.04  1107.1 1113.41  1126.6 1125.15
  1146.1 1130.71  1175.4 1146.75  1194.9 1151.95  1214.4 1162.68  1243.7 1173.14
#Mann= 3 , 0 , 0
       0      .1       0   514.2    .045       0   529.2      .1       0
Bank Sta=514.2,529.2
XS Rating Curve= 0 ,0
Exp/Cntr=0.3,0.1

Type RM Length L Ch R = 1 ,18179.6 ,265.95,263.741,255.216
XS GIS Cut Line= 3
     1695012.744      375411.414     1694753.823      374958.508
     1694415.073      374320.925
#Sta/Elev= 30
       0 1265.85      29 1252.66   135.3 1221.86   183.6 1203.57   212.5 1188.11
   241.5 1177.88   338.1 1134.68   367.1  1127.8   425.1 1123.88   454.1 1118.93
   492.7  1109.1     551 1086.76   602.8 1077.89   609.5  1077.4   617.8  1077.4
   697.3 1087.18   833.9 1081.01   931.5 1079.57   980.3 1081.57  1019.3 1092.95
  1048.5 1109.47  1068.1 1115.18  1087.6 1125.09  1107.1  1131.2  1136.4 1147.07
  1155.9 1152.99  1175.4 1164.67  1194.9 1171.79  1224.2 1188.85  1243.7 1194.54
#Mann= 3 , 0 , 0
       0      .1       0   602.8    .045       0   617.8      .1       0
Bank Sta=602.8,617.8
XS Rating Curve= 0 ,0
Exp/Cntr=0.3,0.1

Type RM Length L Ch R = 1 ,17915.9 ,386.181,400,384.082
XS GIS Cut Line= 3
     1695233.165      375357.368     1694899.095      374733.923
     1694350.832      374108.433
#Sta/Elev= 30
       0 1321.17    29.5 1312.09    58.9 1298.81    78.6 1294.19   186.7 1252.66
   206.3 1247.55   235.8 1232.17   294.7 1208.58   324.2 1191.38   343.8 1184.55
   373.3 1169.64   471.5 1140.61     501 1129.57     560 1116.16   589.4 1099.48
     668 1084.73   699.8 1075.29   707.3  1073.8   714.8 1073.96   805.2 1081.54
   951.9 1083.31  1010.7 1090.35  1079.2 1111.46  1098.7 1115.07  1147.7 1133.59
  1235.7 1175.95  1255.3 1182.43  1294.4 1201.19  1362.9 1226.52  1539.1 1269.03
#Mann= 3 , 0 , 0
       0      .1       0   699.8    .045       0   714.8      .1       0
Bank Sta=699.8,714.8
XS Rating Curve= 0 ,0
Exp/Cntr=0.3,0.1

Type RM Length L Ch R = 1 ,17515.9 ,5730.347,5739.314,5757.485
XS GIS Cut Line= 3
     1695351.569      375323.193     1695186.469      374562.308
     1695046.543      374111.755
#Sta/Elev= 30
       0 1319.19    29.2 1315.64    68.1 1315.44   136.3 1286.17   233.6 1255.66
   311.4 1227.86   340.6 1211.47   360.1 1204.47   379.6 1192.39   389.3 1191.55
   418.5 1173.46   535.3 1125.76   554.7 1120.24   622.9 1088.82   642.3 1084.51
   771.1 1070.98   786.1 1070.65   788.4 1070.64   847.4 1074.96   876.9 1085.15
   896.5 1096.35   916.2 1102.96   945.7 1118.33   994.8 1133.39  1024.3 1147.69
    1044  1153.1  1063.6 1162.29  1102.9 1175.63  1161.9 1187.74  1250.4 1214.32
#Mann= 3 , 0 , 0
       0      .1       0   771.1    .045       0   786.1      .1       0
Bank Sta=771.1,786.1
XS Rating Curve= 0 ,0
Exp/Cntr=0.3,0.1

Type RM Length L Ch R = 1 ,11776.5 ,262.13,260.686,256.592
XS GIS Cut Line= 4
     1699558.413      372176.805     1699545.081      371744.369
     1699470.252      371012.354      1698597.75      369663.059
#Sta/Elev= 30
       0 1178.23   137.7 1160.09   167.2 1138.72   216.3 1117.84   245.8 1097.12
   314.6 1066.55   324.5 1065.96   373.6 1068.01   432.6 1080.42   815.3 1079.29
   962.4 1083.76  1109.6 1165.99  1188.1 1195.97  1315.4 1204.71  1403.6 1219.52
    1482 1222.96  1540.8 1240.48  1609.4 1271.14  1707.3  1305.3  1775.9 1325.45
  1824.9    1334  1844.5 1332.22  1873.9 1339.77  2030.7 1350.43    2207 1387.86
  2275.6  1392.7  2373.6 1379.61  2530.3 1390.79  2628.3 1391.94  2775.3 1373.96
#Mann= 3 , 0 , 0
       0      .1       0   314.6    .045       0   373.6      .1       0
Bank Sta=314.6,373.6
XS Rating Curve= 0 ,0
Exp/Cntr=0.3,0.1

Type RM Length L Ch R = 1 ,11515.9 ,403.039,408.723,417.057
XS GIS Cut Line= 3
      1699834.03      371816.206     1699760.329      371369.808
       1699630.9      370919.131
#Sta/Elev= 30
       0  1063.3    39.3 1061.58   108.2 1061.47   186.9 1066.64   265.6 1062.68
   304.9 1055.48   324.6 1049.24   442.6 1028.08   444.9 1028.09   459.9 1028.77
   481.7 1037.42   491.5 1038.33   520.8 1052.26   540.4 1058.55   559.9 1067.96
   579.4 1073.65   608.7 1090.17   628.3 1097.76   647.8 1107.99   657.6 1109.49
   686.9 1126.49   706.4 1133.15     726 1143.86   735.7 1145.43   774.8 1159.74
   804.1 1172.92   823.6 1178.67   843.2 1187.14   882.3    1195   921.3 1193.96
#Mann= 3 , 0 , 0
       0      .1       0   444.9    .045       0   459.9      .1       0
Bank Sta=444.9,459.9
XS Rating Curve= 0 ,0
Exp/Cntr=0.3,0.1

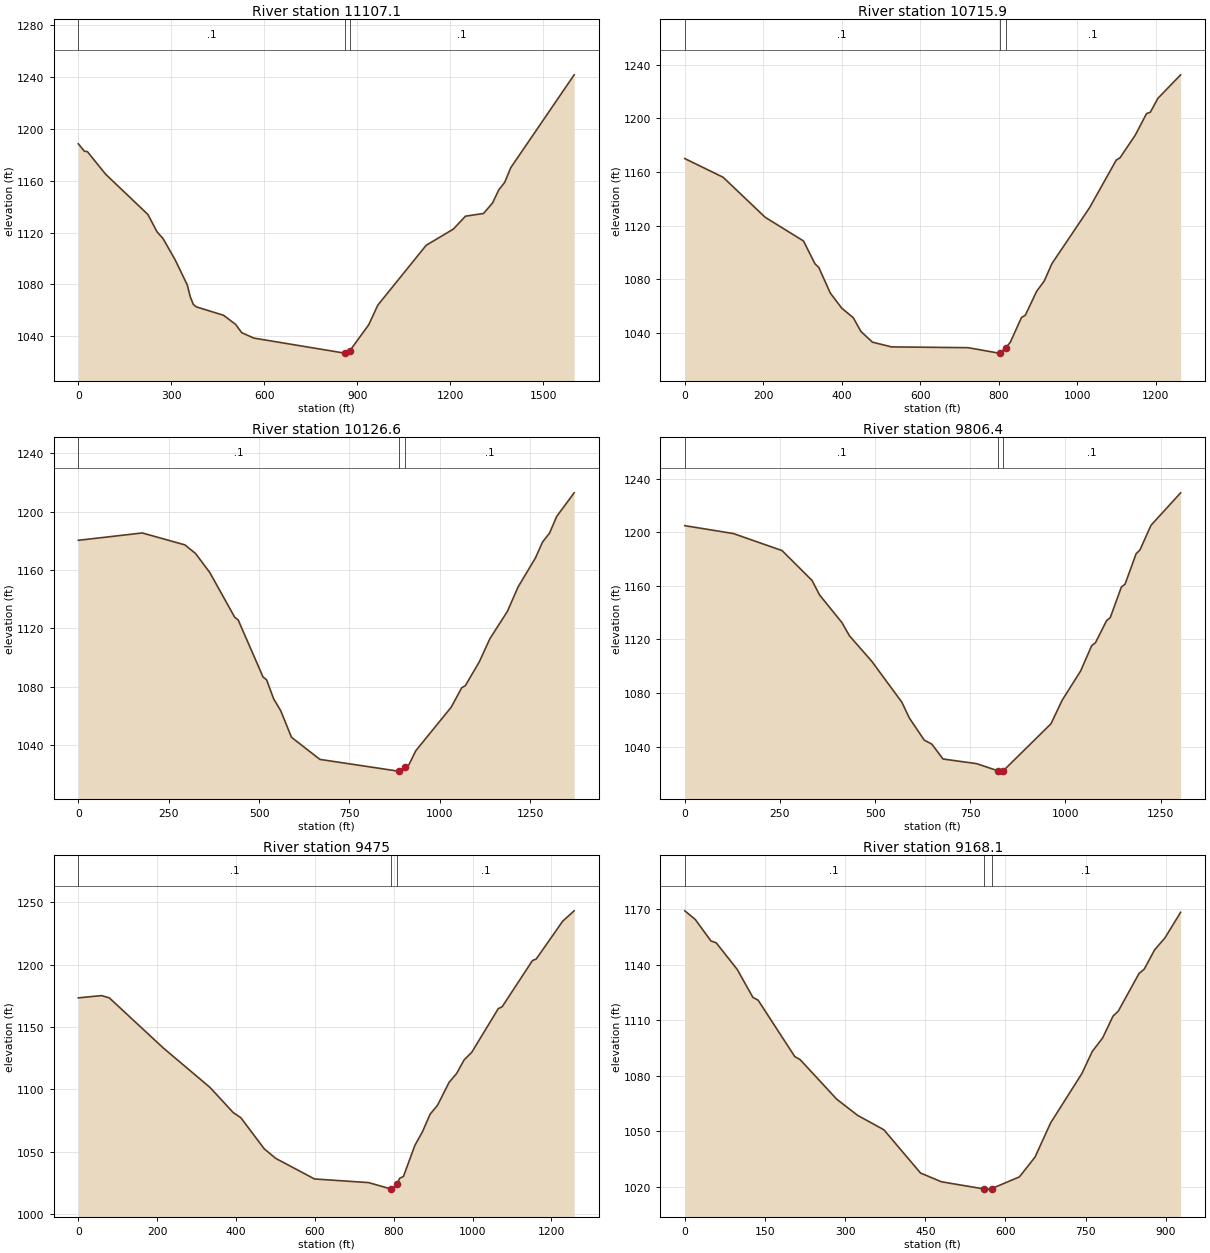
Type RM Length L Ch R = 1 ,11107.1 ,387.451,391.277,392.182
XS GIS Cut Line= 3
     1699997.541      372098.111     1700120.939       371267.23
     1700194.978      370510.387
#Sta/Elev= 30
       0 1188.49    19.5  1182.8    29.3 1182.47    87.9  1165.1   224.6 1133.96
     254 1120.58   273.5 1115.35   312.6 1098.92   351.6 1079.64   361.4 1070.41
   371.2 1064.53   380.9 1062.65   468.8 1056.16   507.9 1049.07   527.4 1042.73
   566.5 1038.55   859.5 1026.95   861.9 1027.02   876.9 1028.94   937.5 1048.92
   966.7    1064  1122.7 1110.17  1210.5 1122.69  1249.5 1132.64    1308 1134.76
  1337.2  1142.9  1356.7  1152.8  1376.2 1158.74  1395.7 1170.05  1600.4 1241.75
#Mann= 3 , 0 , 0
       0      .1       0   861.9    .045       0   876.9      .1       0
Bank Sta=861.9,876.9
XS Rating Curve= 0 ,0
Exp/Cntr=0.3,0.1

Type RM Length L Ch R = 1 ,10715.9 ,596.951,589.262,583.848
XS GIS Cut Line= 3
     1700289.583      372085.771     1700492.893      371301.744
     1700550.718      370851.672
#Sta/Elev= 30
       0 1170.01    97.6 1156.06   204.9 1126.15   302.5 1108.45   331.8 1091.41
   341.5 1088.68   370.8 1069.58   400.1 1058.25   429.4 1051.14   448.9 1040.86
   478.2 1032.88     527 1029.33   722.1 1028.75   800.2 1024.68   802.5 1024.73
   817.5 1028.58   829.3 1032.62   858.2 1051.31   867.9 1052.99   896.9 1070.96
   916.2 1078.56   935.5 1091.45    1032 1133.49  1099.6 1168.86  1109.3 1170.63
  1147.9 1187.41  1176.8 1203.57  1186.5 1204.66  1205.8 1215.02  1263.7 1232.56
#Mann= 3 , 0 , 0
       0      .1       0   802.5    .045       0   817.5      .1       0
Bank Sta=802.5,817.5
XS Rating Curve= 0 ,0
Exp/Cntr=0.3,0.1

Type RM Length L Ch R = 1 ,10126.6 ,316.276,320.232,324.34
XS GIS Cut Line= 3
     1701054.652      372340.794     1700980.613      371341.269
     1700966.258      370972.323
#Sta/Elev= 30
       0 1180.41   176.9 1185.45   294.8 1177.28   324.3 1171.35   363.6 1158.35
   432.3 1127.78   442.2  1125.8     511 1086.69   520.8 1084.78   540.4 1071.66
   560.1 1063.48   589.6 1045.39   668.2 1030.22   884.4 1022.18   887.6 1022.26
   902.6 1024.86   913.8 1026.29   933.5 1036.18  1031.4 1066.01  1060.6 1079.39
  1070.3  1080.7  1109.1 1097.07  1138.3 1112.91  1186.9 1131.72    1216 1148.24
  1264.6 1168.42    1284 1179.21  1303.5 1185.33  1322.9 1196.66  1371.5 1212.96
#Mann= 3 , 0 , 0
       0      .1       0   887.6    .045       0   902.6      .1       0
Bank Sta=887.6,902.6
XS Rating Curve= 0 ,0
Exp/Cntr=0.3,0.1

Type RM Length L Ch R = 1 ,9806.4  ,341.607,331.41,320.644
XS GIS Cut Line= 3
     1701264.429       372349.02     1701284.375      371533.234
     1701321.173      371048.061
#Sta/Elev= 30
       0 1205.04   127.8 1199.14   255.6 1186.41   334.3  1164.1   353.9 1153.35
   412.9 1132.61   432.6 1122.76   491.6 1103.58   570.2 1073.17   589.9 1061.35
   629.2 1044.77   648.9 1041.86   678.4 1030.72   766.9 1027.23   822.2 1021.95
   825.8 1021.66   837.2 1022.08     962 1057.04   991.2 1074.53  1039.9 1096.47
    1069  1115.4  1078.8 1117.55    1108 1134.05  1117.7 1136.32  1146.9 1159.18
  1156.6 1161.34  1185.8 1184.13  1195.6 1186.82  1224.7 1205.29  1302.6 1229.57
#Mann= 3 , 0 , 0
       0      .1       0   822.2    .045       0   837.2      .1       0
Bank Sta=822.2,837.2
XS Rating Curve= 0 ,0
Exp/Cntr=0.3,0.1

Type RM Length L Ch R = 1 ,9475    ,303.76,306.847,309.803
XS GIS Cut Line= 3
     1701897.873      372155.697     1701589.377      371390.628
     1701439.247      370984.524
#Sta/Elev= 30
       0 1173.45    58.9 1175.26    78.6 1173.45   216.1 1133.09   333.9 1101.66
   392.8 1081.49   412.5 1077.24   471.4 1052.45   500.8  1044.7   599.1 1028.19
   736.5 1025.26   793.5 1020.12   795.5 1020.03   808.5 1023.99   815.1 1028.69
   824.9 1030.22   853.8 1055.13     873 1066.01   892.3 1080.02   911.5 1087.43
   940.4 1105.58   959.6 1112.71   978.9 1123.76   998.1 1129.79  1065.5 1164.83
  1075.1 1166.26  1152.1 1203.36  1161.7 1204.63    1229 1235.02  1257.9 1243.26
#Mann= 3 , 0 , 0
       0      .1       0   793.5    .045       0   808.5      .1       0
Bank Sta=793.5,808.5
XS Rating Curve= 0 ,0
Exp/Cntr=0.3,0.1

Type RM Length L Ch R = 1 ,9168.1  ,558.862,570.362,581.405
XS GIS Cut Line= 3
     1701973.443      371952.328     1701929.243      371503.551
        1701816.      371040.417
#Sta/Elev= 30
       0 1169.19    19.6 1164.52      49 1152.87    58.8 1151.88      98 1137.53
   127.4 1122.38   137.2 1120.83   205.9 1090.26   215.7 1088.69   284.3 1067.25
   323.5 1058.47   372.5 1050.71   441.1 1027.28   480.1 1022.56   559.1 1018.71
   567.7 1018.58   574.1 1018.85   626.1 1025.22   655.3 1035.92   684.5 1054.44
   742.9 1081.11   762.3 1093.04   781.8 1100.41   801.2 1112.21     811 1114.89
   849.9 1135.28   859.6 1137.64   879.1 1148.11   898.5  1154.6   927.7 1168.39
#Mann= 3 , 0 , 0
       0      .1       0   559.1    .045       0   574.1      .1       0
Bank Sta=559.1,574.1
XS Rating Curve= 0 ,0
Exp/Cntr=0.3,0.1

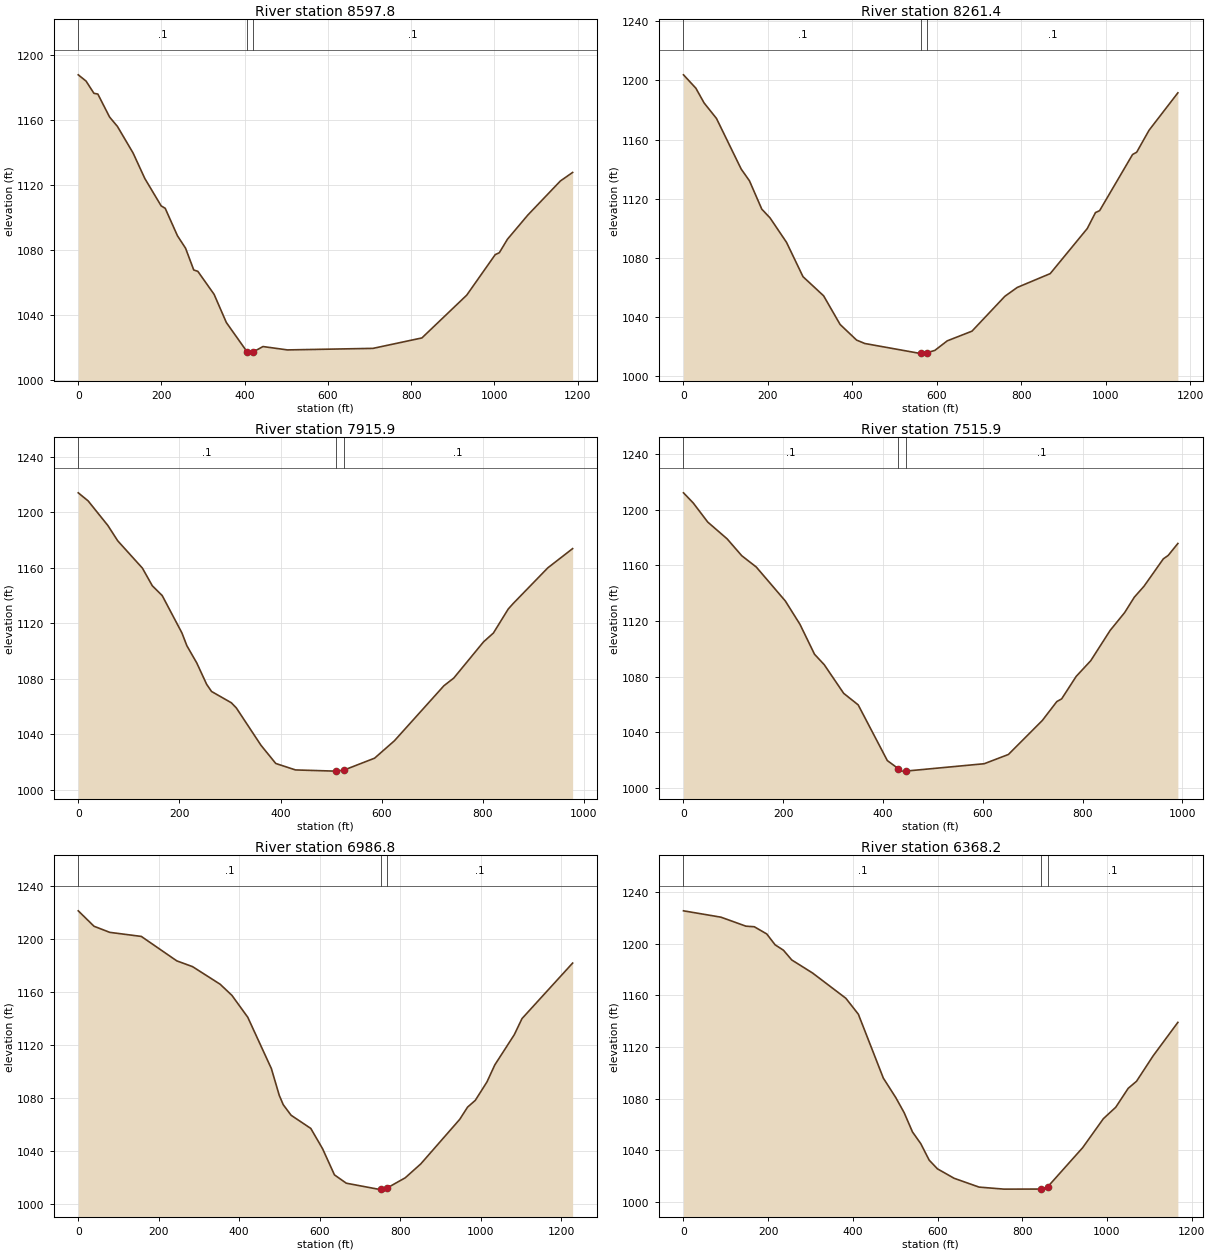
Type RM Length L Ch R = 1 ,8597.8  ,336.821,336.392,337.291
XS GIS Cut Line= 3
     1702340.092      371820.256     1702367.667      371662.654
     1702578.577      370656.618
#Sta/Elev= 30
       0 1187.91    18.8 1184.04    37.6 1176.53    47.1 1176.05    75.3 1161.87
    94.1 1156.11   131.8 1139.69     160 1123.96   199.2 1107.12   208.9 1105.64
   238.3 1088.72   257.9    1081   277.5  1067.6   287.3 1066.77   326.4 1052.59
   355.8 1035.23   405.9 1017.05   414.5 1016.34   420.9 1017.17   443.9  1020.4
   502.6 1018.32   708.2 1019.27   825.7  1025.7   933.4 1052.07  1001.9 1077.06
  1011.7 1078.23  1031.3 1086.56  1080.2 1101.45  1158.5 1122.48  1187.9 1127.73
#Mann= 3 , 0 , 0
       0      .1       0   405.9    .045       0   420.9      .1       0
Bank Sta=405.9,420.9
XS Rating Curve= 0 ,0
Exp/Cntr=0.3,0.1

Type RM Length L Ch R = 1 ,8261.4  ,328.174,345.496,356.599
XS GIS Cut Line= 3
     1702412.082      371906.031     1702678.824      371406.765
     1702937.798      370860.397
#Sta/Elev= 30
       0  1203.7    29.3 1194.66    48.8  1184.7    78.1 1174.23   136.6 1140.05
   156.2 1132.11   185.4 1112.97     205 1107.03     244 1090.52     283 1067.34
   331.8 1054.42   370.9 1035.05   409.9 1024.51   429.4  1022.2   556.3  1015.7
   562.7  1015.7   577.7 1016.06   595.3 1017.56   624.6    1024   683.1 1030.53
   761.1 1054.11   790.4 1060.08   868.4 1069.41   956.1 1099.85   975.6 1110.65
   985.4 1111.94  1063.4 1149.87  1073.2 1151.43  1102.4 1166.23  1170.7 1191.53
#Mann= 3 , 0 , 0
       0      .1       0   562.7    .045       0   577.7      .1       0
Bank Sta=562.7,577.7
XS Rating Curve= 0 ,0
Exp/Cntr=0.3,0.1

Type RM Length L Ch R = 1 ,7915.9  ,399.605,400,399.636
XS GIS Cut Line= 3
      1702401.19      371938.566     1702844.004      371670.752
     1703205.894      371386.515
#Sta/Elev= 30
       0 1214.04    19.5 1208.24    58.6 1190.48    78.1 1179.45   126.9 1159.77
   146.5 1147.05     166 1140.03     205 1113.11   214.8 1103.88   234.3 1091.52
   253.9 1076.08   263.6 1070.92   302.7 1062.79   312.5 1059.13   361.3 1032.19
   390.6 1019.04   429.6 1014.39   507.7 1013.53     510 1013.56     525 1014.22
     586 1022.85   625.2 1035.38   723.1 1075.03   742.7  1080.6   801.4 1106.62
     821 1113.02   850.4 1130.35   860.2 1134.32   928.7 1160.02   977.7 1173.85
#Mann= 3 , 0 , 0
       0      .1       0     510    .045       0     525      .1       0
Bank Sta=510,525
XS Rating Curve= 0 ,0
Exp/Cntr=0.3,0.1

Type RM Length L Ch R = 1 ,7515.9  ,516.117,529.097,539.158
XS GIS Cut Line= 3
     1702589.996      372277.073     1702953.792      372033.736
     1703337.856       371635.63
#Sta/Elev= 30
       0 1212.08    19.5 1204.79    48.6 1191.05    87.5 1178.96   116.7 1166.88
   145.9 1158.71   204.2 1134.26   233.4 1117.54   262.6 1096.01   282.1 1088.48
     321 1067.92   350.1 1059.61   408.5 1019.56   430.2 1013.83   437.7 1011.97
   445.2 1011.98   602.7 1017.29   651.2 1023.95   719.1 1048.38   748.2 1061.98
   757.9 1063.94     787 1080.08   816.2 1091.38     855 1113.11   884.1 1125.95
   903.5 1137.04   922.9 1144.89   961.7 1164.62   971.4 1167.06   990.8 1175.66
#Mann= 3 , 0 , 0
       0      .1       0   430.2    .045       0   445.2      .1       0
Bank Sta=430.2,445.2
XS Rating Curve= 0 ,0
Exp/Cntr=0.3,0.1

Type RM Length L Ch R = 1 ,6986.8  ,626.529,618.579,610.711
XS GIS Cut Line= 3
     1702588.903      372558.797     1703312.839      372258.528
     1703698.589      372036.574
#Sta/Elev= 30
       0  1221.3    39.2 1209.64    78.4 1205.03   156.7 1201.97   244.9  1183.5
   284.1 1179.14   352.7 1165.85   382.1 1157.39   421.3 1140.92     480 1102.13
   499.6 1081.94   509.4 1074.92     529  1066.9     578 1056.93   607.4 1041.54
   636.8 1021.85   666.2 1015.57   744.6 1011.09   752.7 1011.11   767.7 1011.95
   812.8 1019.66   851.5 1030.19   948.2  1063.8   967.6 1073.02   986.9 1078.16
  1015.9 1092.08  1035.3 1104.89  1083.7 1127.69    1103 1139.92  1228.8 1181.83
#Mann= 3 , 0 , 0
       0      .1       0   752.7    .045       0   767.7      .1       0
Bank Sta=752.7,767.7
XS Rating Curve= 0 ,0
Exp/Cntr=0.3,0.1

Type RM Length L Ch R = 1 ,6368.2  ,519.886,505.785,491.685
XS GIS Cut Line= 3
     1702905.625      373204.581     1703510.276      372817.934
     1703838.665      372510.639
#Sta/Elev= 30
       0 1225.31    88.5 1220.39   147.5 1213.43   167.1    1213   196.6 1207.43
   216.3 1199.03     236 1194.85   255.6 1187.33   304.8 1177.22   383.4 1157.68
   412.9 1145.37   471.9 1095.94   501.4 1080.82   521.1 1069.18   540.7 1054.34
   560.4  1045.2   580.1 1032.53   599.7 1025.77   639.1 1018.47     698 1011.65
   756.8 1010.09     845 1010.14     860 1011.86   942.6 1042.15   991.5 1064.56
  1020.8 1073.45  1050.1 1088.04  1069.7 1093.48  1108.8 1113.07  1167.4 1139.05
#Mann= 3 , 0 , 0
       0      .1       0     845    .045       0     860      .1       0
Bank Sta=845,860
XS Rating Curve= 0 ,0
Exp/Cntr=0.3,0.1

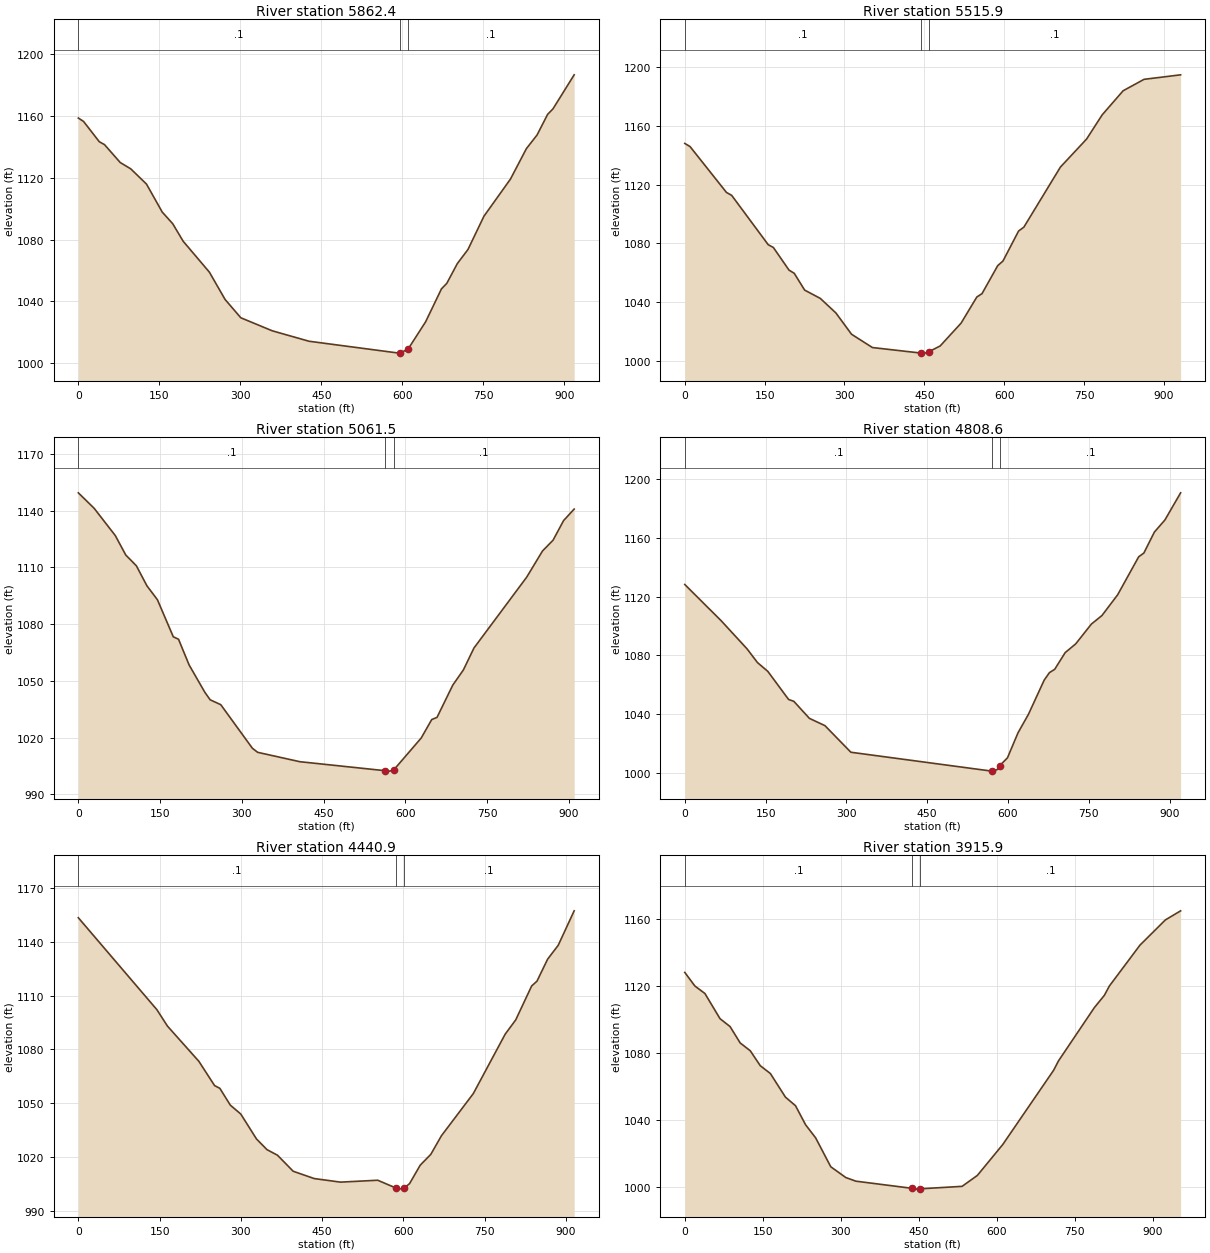
Type RM Length L Ch R = 1 ,5862.4  ,352.24,346.538,344.325
XS GIS Cut Line= 3
     1703962.663      373527.468     1703981.057      373071.759
     1704071.198      372618.784
#Sta/Elev= 30
       0 1158.79     9.7 1156.58    38.8 1143.43    48.5 1141.53    77.6 1129.93
      97 1125.85   126.2 1115.95   155.3 1097.83   174.7 1090.27   194.1 1078.89
   242.6 1058.87   271.7 1041.14   300.8 1029.27     359 1020.83     427 1014.06
   593.7 1006.35   595.3 1006.41   610.3 1008.89   642.8 1026.57   672.3 1048.05
   682.1 1051.58   701.7 1064.45   721.4 1073.59   750.9 1095.13     800 1119.21
   829.5 1138.96   849.2 1147.77   868.8 1161.17   878.6 1164.69   917.9  1186.8
#Mann= 3 , 0 , 0
       0      .1       0   595.3    .045       0   610.3      .1       0
Bank Sta=595.3,610.3
XS Rating Curve= 0 ,0
Exp/Cntr=0.3,0.1

Type RM Length L Ch R = 1 ,5515.9  ,447.898,454.335,457.283
XS GIS Cut Line= 3
     1704358.964      373484.137      1704332.96        373034.5
     1704379.102      372555.584
#Sta/Elev= 30
       0 1148.12     9.8 1146.01    78.3 1114.74    88.1 1112.75   156.7 1079.16
   166.4 1077.26   195.8 1061.84   205.6 1059.67   225.2 1048.22   254.6 1042.57
   283.9 1032.65   313.3 1018.15   352.5  1009.1   442.9 1005.37   450.4  1005.3
   457.9 1006.14   479.8  1010.2   519.1 1025.75   548.6 1043.51   558.4 1045.83
   587.9  1064.9   597.7 1068.01   627.1 1088.47     637  1091.1   705.7 1132.03
   754.8 1151.09   784.2 1167.61   823.5    1184   862.8 1191.78   931.5 1194.85
#Mann= 3 , 0 , 0
       0      .1       0   442.9    .045       0   457.9      .1       0
Bank Sta=442.9,457.9
XS Rating Curve= 0 ,0
Exp/Cntr=0.3,0.1

Type RM Length L Ch R = 1 ,5061.5  ,250.753,252.924,255.096
XS GIS Cut Line= 3
     1704655.662       373528.73     1704755.634      373084.849
     1704855.606      372640.967
#Sta/Elev= 30
       0 1149.43      29 1141.27    67.8 1126.86    87.1 1116.55   106.5 1110.88
   125.9 1100.28   145.2 1092.91   174.3 1073.32   183.9 1072.05   203.3 1058.47
   232.3 1043.95     242 1040.02   261.4 1037.46   319.5  1014.4   329.1 1012.27
   406.6 1007.31   563.5 1002.54   571.2 1002.33   578.5 1002.84   629.3 1019.84
   648.6 1029.58   658.3 1030.74   687.3 1047.82   706.7 1055.82   726.1  1067.4
   822.9 1104.86   851.9 1118.69   871.3  1124.4   890.6 1134.76     910 1140.84
#Mann= 3 , 0 , 0
       0      .1       0   563.5    .045       0   578.5      .1       0
Bank Sta=563.5,578.5
XS Rating Curve= 0 ,0
Exp/Cntr=0.3,0.1

Type RM Length L Ch R = 1 ,4808.6  ,377.123,367.681,358.238
XS GIS Cut Line= 3
     1704753.397      373523.749     1704985.748      373135.006
     1705135.847      372692.218
#Sta/Elev= 30
       0 1128.16    67.5 1103.58   115.6 1084.46   134.9 1075.17   154.2 1069.15
   192.7  1050.1   202.4 1048.84   231.3 1037.29   260.2 1032.32   308.3 1014.27
   569.8 1001.45     570 1001.47   579.5 1002.38     585 1005.27     599 1010.51
   618.5 1027.44     638  1040.1   667.2 1063.28   676.9 1068.34   686.7  1070.6
   706.1 1081.93   725.6 1087.84   754.8 1101.32   774.3 1107.08   803.5 1121.18
   842.5 1146.96   852.2 1149.57   871.7 1163.77   891.2 1171.97   920.4 1190.42
#Mann= 3 , 0 , 0
       0      .1       0     570    .045       0     585      .1       0
Bank Sta=570,585
XS Rating Curve= 0 ,0
Exp/Cntr=0.3,0.1

Type RM Length L Ch R = 1 ,4440.9  ,532.621,525.06,512.049
XS GIS Cut Line= 3
      1705418.97      373678.157     1705387.721      373224.682
     1705345.838      372766.124
#Sta/Elev= 30
       0 1153.44   145.1 1102.11   164.4 1093.03   222.4 1073.37   251.5  1059.8
   261.1 1058.31   280.5 1048.91   299.8 1043.95   328.8 1030.04   348.2 1024.08
   367.5 1020.99   396.5 1012.04   435.2 1007.97   483.9 1005.97   552.5 1007.03
   586.2 1002.68   591.7 1002.07   601.2 1002.64   611.3 1005.15   630.9 1015.42
   650.5 1021.48   670.1 1031.85   728.9 1055.37   787.7 1088.49   807.2 1096.48
   836.6 1115.39   846.4 1118.06     866 1130.31   885.6 1138.07     915 1157.29
#Mann= 3 , 0 , 0
       0      .1       0   586.2    .045       0   601.2      .1       0
Bank Sta=586.2,601.2
XS Rating Curve= 0 ,0
Exp/Cntr=0.3,0.1

Type RM Length L Ch R = 1 ,3915.9  ,416.437,399.767,387.735
XS GIS Cut Line= 3
     1706057.557      373409.812     1705873.751      373004.143
     1705563.702      372601.214
#Sta/Elev= 30
       0 1128.16    19.4 1120.05    38.7 1115.57    67.8 1100.51    87.1  1095.8
   106.5 1086.03   125.9 1081.36   145.2 1072.41   164.6 1067.75   193.6 1053.63
     213 1048.49   232.4 1037.09   251.7  1029.3   280.8 1012.01   309.8 1005.55
   329.2 1003.39   437.9  999.09   445.4  998.64   452.9  998.83   533.4  1000.3
   562.7  1006.8   611.6 1025.28   709.4 1069.64   719.1  1075.4   787.6 1107.02
   807.1 1114.48   816.9 1120.11   875.6 1144.47   924.4 1159.53   953.8 1164.98
#Mann= 3 , 0 , 0
       0      .1       0   437.9    .045       0   452.9      .1       0
Bank Sta=437.9,452.9
XS Rating Curve= 0 ,0
Exp/Cntr=0.3,0.1

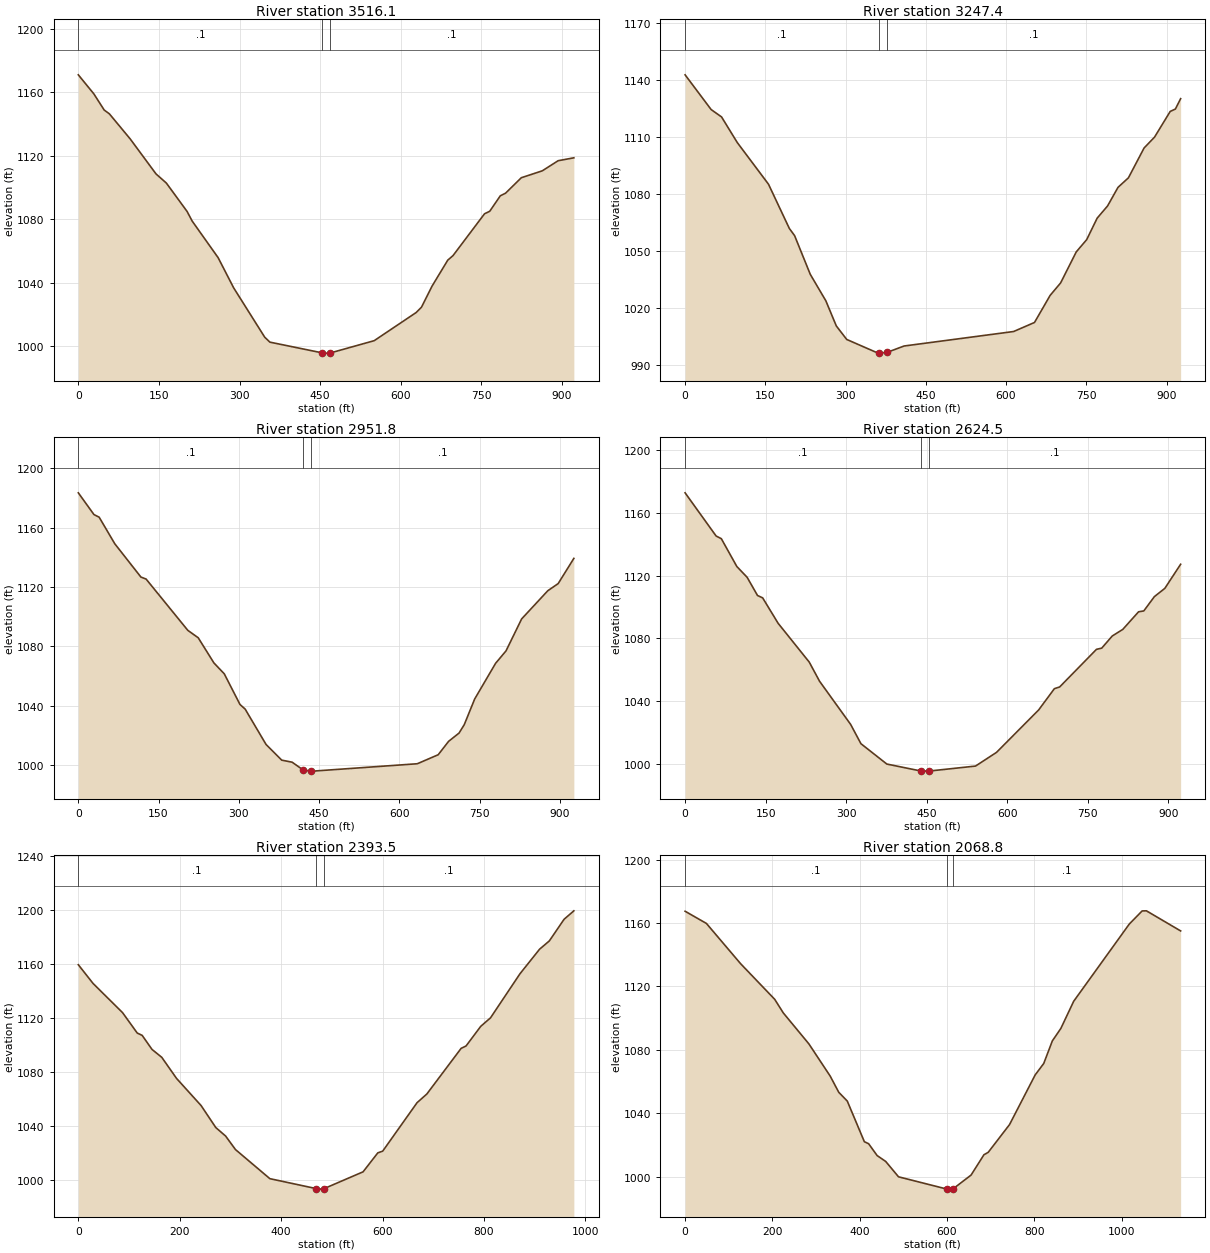
Type RM Length L Ch R = 1 ,3516.1  ,255.78,268.669,283.005
XS GIS Cut Line= 3
     1706476.674      372898.635     1706060.639      372696.281
     1705643.038      372504.166
#Sta/Elev= 30
       0 1171.06    28.9 1159.07    48.2 1148.89    57.8  1146.5    96.4 1130.77
   144.6 1108.67   163.9 1102.89   202.4 1085.05     212 1078.93   260.2 1055.94
   289.1 1036.94     347 1005.83   356.6 1002.73   454.2  995.96   462.6  995.82
   469.2  995.94   550.7 1003.66   628.9 1021.41   638.7 1024.74   658.2 1037.91
   687.6 1054.36   697.4 1057.23     756 1083.55   765.8 1085.17   785.4 1094.89
   795.2 1096.53   824.5 1106.26   863.6 1110.62     893 1116.97   922.3 1118.81
#Mann= 3 , 0 , 0
       0      .1       0   454.2    .045       0   469.2      .1       0
Bank Sta=454.2,469.2
XS Rating Curve= 0 ,0
Exp/Cntr=0.3,0.1

Type RM Length L Ch R = 1 ,3247.4  ,295.049,295.675,295.464
XS GIS Cut Line= 3
     1706428.714      372846.592     1706194.787      372441.356
     1705971.999      372040.659
#Sta/Elev= 30
       0 1142.53    48.7 1124.29    68.2  1120.4    97.5 1106.98     156 1085.04
     195 1061.78   204.7 1058.09     234 1037.76   263.2 1023.81   282.7 1010.64
   302.2 1003.54   360.7  996.36   362.4  996.38   377.4  996.74   409.4  1000.1
   614.2 1007.71   653.2 1012.46   682.5 1026.71     702 1033.22   731.3 1049.54
   750.8 1055.98   770.3 1067.22   789.8 1073.66   809.3 1083.42   828.8 1088.44
   858.1 1104.11   877.6  1109.8   906.9  1123.3   916.6 1124.56   926.4 1130.01
#Mann= 3 , 0 , 0
       0      .1       0   362.4    .045       0   377.4      .1       0
Bank Sta=362.4,377.4
XS Rating Curve= 0 ,0
Exp/Cntr=0.3,0.1

Type RM Length L Ch R = 1 ,2951.8  ,308.835,327.289,339.296
XS GIS Cut Line= 3
     1706682.104      372741.702     1706448.177      372336.467
     1706225.389       371935.77
#Sta/Elev= 30
       0 1183.41    29.2 1168.77      39 1166.96    68.2 1149.06     117 1126.63
   126.7 1125.28   204.7  1090.7   224.2 1085.68   253.5 1068.73   272.9 1061.37
   302.2 1040.75   311.9 1037.61   350.9 1013.81   380.2  1003.2   399.7 1001.82
   420.3  996.58   435.3   995.8   438.7  995.79   633.7 1000.76   672.8 1006.84
   692.3 1015.89   711.8 1021.46   721.5 1027.12     741 1044.43   780.1 1068.48
   799.6 1076.86   828.8 1098.41   877.6 1117.37   897.1 1122.23   926.4 1139.22
#Mann= 3 , 0 , 0
       0      .1       0   420.3    .045       0   435.3      .1       0
Bank Sta=420.3,435.3
XS Rating Curve= 0 ,0
Exp/Cntr=0.3,0.1

Type RM Length L Ch R = 1 ,2624.5  ,231.941,230.993,236.359
XS GIS Cut Line= 3
     1706741.842      372696.808     1706756.917      372244.166
     1706738.405      371774.223
#Sta/Elev= 30
       0 1172.78    57.8 1145.21    67.5 1143.52    96.4 1125.75   115.6 1118.85
   134.9 1107.26   144.5 1105.74   173.4 1089.47   231.3 1064.74   250.5 1052.53
   308.4 1024.98   327.6 1012.66   375.8  999.67   438.7  995.27   452.9  995.15
   453.7  995.16   541.1  998.38   580.3 1007.15   658.7  1034.2     688 1047.78
   697.8 1048.87   766.4 1072.88   776.2 1073.65   795.8  1081.4   815.4  1085.6
   844.8 1096.84   854.6 1097.41   874.2  1106.5   893.8 1111.82   923.2 1127.19
#Mann= 3 , 0 , 0
       0      .1       0   438.7    .045       0   453.7      .1       0
Bank Sta=438.7,453.7
XS Rating Curve= 0 ,0
Exp/Cntr=0.3,0.1

Type RM Length L Ch R = 1 ,2393.5  ,317.588,324.662,331.021
XS GIS Cut Line= 3
     1706876.161      372704.126     1706986.654      372212.852
     1707104.695      371754.205
#Sta/Elev= 30
       0  1159.4    29.1 1145.53    87.2 1123.95   116.2 1108.82   125.9 1107.11
   145.3 1096.72   164.6 1090.84   193.7 1075.25   242.1 1055.16   271.1 1038.88
   290.5 1032.57   309.9 1022.59   377.7 1001.05   468.9  993.71   474.5  993.31
   483.9  993.57   561.5 1006.12   590.5 1020.14   600.2 1021.43   667.9 1057.27
   687.2 1063.71   754.8 1097.49   764.5 1099.25   793.5  1113.8   812.8  1120.1
   870.8 1152.68   909.5 1170.88   928.8 1177.04   957.8 1193.02   977.1 1199.29
#Mann= 3 , 0 , 0
       0      .1       0   468.9    .045       0   483.9      .1       0
Bank Sta=468.9,483.9
XS Rating Curve= 0 ,0
Exp/Cntr=0.3,0.1

Type RM Length L Ch R = 1 ,2068.8  ,641.276,634.408,623.691
XS GIS Cut Line= 3
     1706934.603      372859.793      1707266.99       372329.48
     1707459.215       371857.62
#Sta/Elev= 30
       0 1167.42    48.9 1159.71   127.1 1134.35   205.4 1111.82   224.9  1103.3
   283.6 1083.74   332.5 1063.38   352.1 1053.18   371.6 1047.64   410.7 1022.02
   420.5 1020.72   440.1 1013.23   459.6 1009.56     489  999.85   599.6  992.13
   606.3  992.08   614.6  992.38   655.3 1000.96   684.7 1013.77   694.5 1015.29
   743.4 1032.82   802.2 1064.18   821.8 1071.39   841.4 1085.58     861 1093.49
   890.4 1110.63  1017.8 1159.35  1047.2 1167.61    1057 1167.68  1135.4    1155
#Mann= 3 , 0 , 0
       0      .1       0   599.6    .045       0   614.6      .1       0
Bank Sta=599.6,614.6
XS Rating Curve= 0 ,0
Exp/Cntr=0.3,0.1

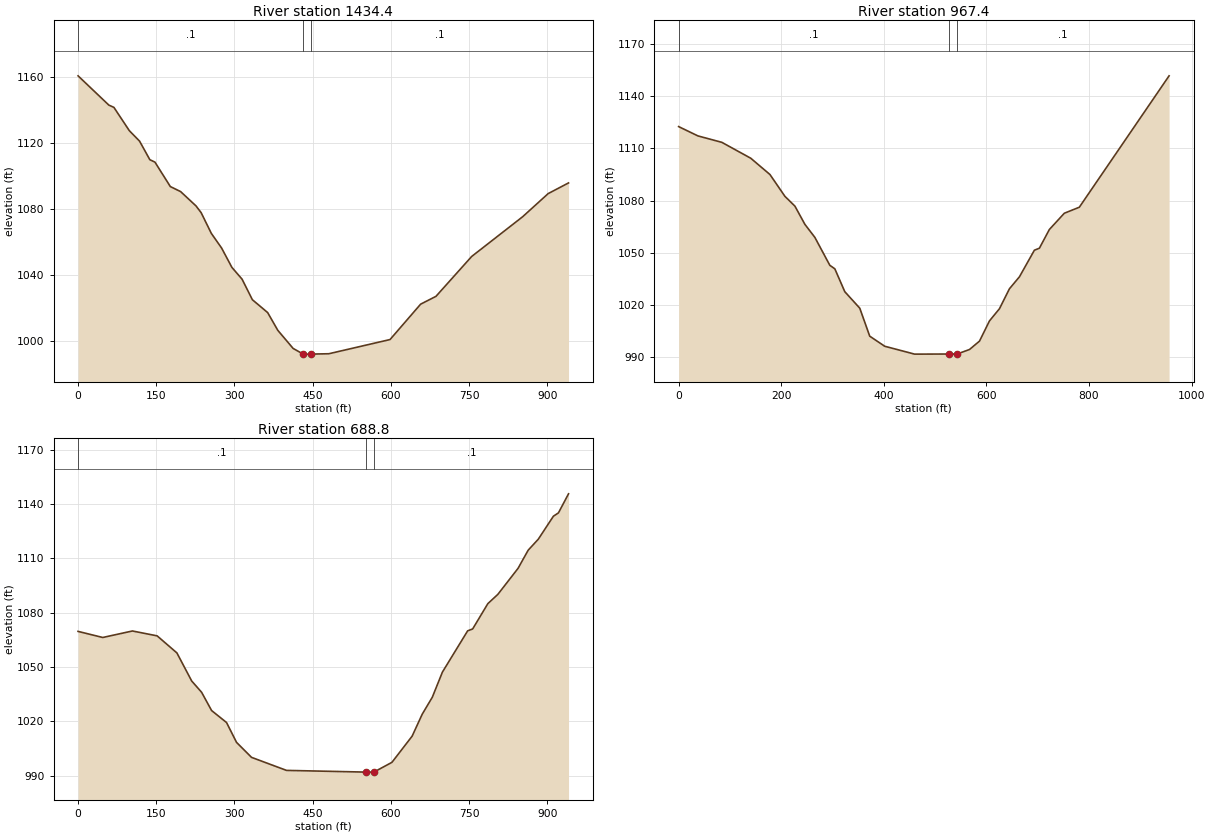
Type RM Length L Ch R = 1 ,1434.4  ,393.57,466.982,394.183
XS GIS Cut Line= 3
     1707644.074      373000.609     1707717.003      372684.337
     1707882.952       372090.72
#Sta/Elev= 30
       0 1160.56      59 1142.83    68.8 1141.42    98.4  1127.3     118 1120.97
   137.7 1109.72   147.5 1108.25     177 1093.44   196.7  1090.4   226.2 1081.73
   236.1 1077.63   255.7 1065.04   275.4 1056.16   295.1 1044.46   314.7 1037.27
   334.4 1024.85   363.7 1017.06   383.3 1006.25   412.6  995.32     432  991.88
   432.2  991.87     447  991.89   481.1   992.1   598.5 1000.71   657.2 1022.16
   686.6 1026.89   755.1 1051.06   852.9 1075.15   901.8 1089.16   940.9 1095.64
#Mann= 3 , 0 , 0
       0      .1       0     432    .045       0     447      .1       0
Bank Sta=432,447
XS Rating Curve= 0 ,0
Exp/Cntr=0.3,0.1

Type RM Length L Ch R = 1 ,967.4   ,337.981,278.588,280.239
XS GIS Cut Line= 3
     1707921.146       373005.01     1708010.196       372850.84
     1708148.983      372085.363
#Sta/Elev= 30
       0 1122.41    37.5 1117.08    84.3 1113.37   140.6 1104.26     178 1094.92
   207.2  1082.4   226.7 1076.78   246.1 1066.35   265.6 1058.84   294.7 1042.85
   304.5 1040.81   323.9  1027.7   353.1 1018.24   372.5 1002.19   401.7  996.41
     460  991.89   527.8  991.95   542.8  991.95     567  994.55   586.5  999.37
   605.9 1010.95   625.4 1017.95   644.8 1029.37   664.3 1036.24   693.4 1051.49
   703.2 1052.65   722.6 1063.36   751.8 1072.71     781 1076.15     956 1151.53
#Mann= 3 , 0 , 0
       0      .1       0   527.8    .045       0   542.8      .1       0
Bank Sta=527.8,542.8
XS Rating Curve= 0 ,0
Exp/Cntr=0.3,0.1

Type RM Length L Ch R = 1 ,688.8   ,708.943,688.829,668.715
XS GIS Cut Line= 4
     1708125.368      372978.351     1708283.457      372801.838
     1708332.339      372557.672     1708445.865      372117.213
#Sta/Elev= 30
       0 1069.69    47.4 1066.32   104.3 1069.92   151.7 1067.22   189.6 1057.79
     218 1042.26     237 1036.03   256.1 1025.95   284.8 1019.31     304 1008.34
   332.7 1000.06   399.8  992.85   552.7   991.9   553.7  991.89   567.7  991.94
   602.1  997.31   640.8 1011.77   660.2 1023.93   679.5 1033.28   698.9 1047.19
   747.3 1069.99   756.9 1071.04     786 1085.01   805.3 1090.18     844 1104.55
   863.4 1114.58   882.8 1120.65   911.8 1133.37   921.5 1135.22   940.8 1145.74
#Mann= 3 , 0 , 0
       0      .1       0   552.7    .045       0   567.7      .1       0
Bank Sta=552.7,567.7
XS Rating Curve= 0 ,0
Exp/Cntr=0.3,0.1

Chan Stop Cuts=-1
Use User Specified Reach Order=0